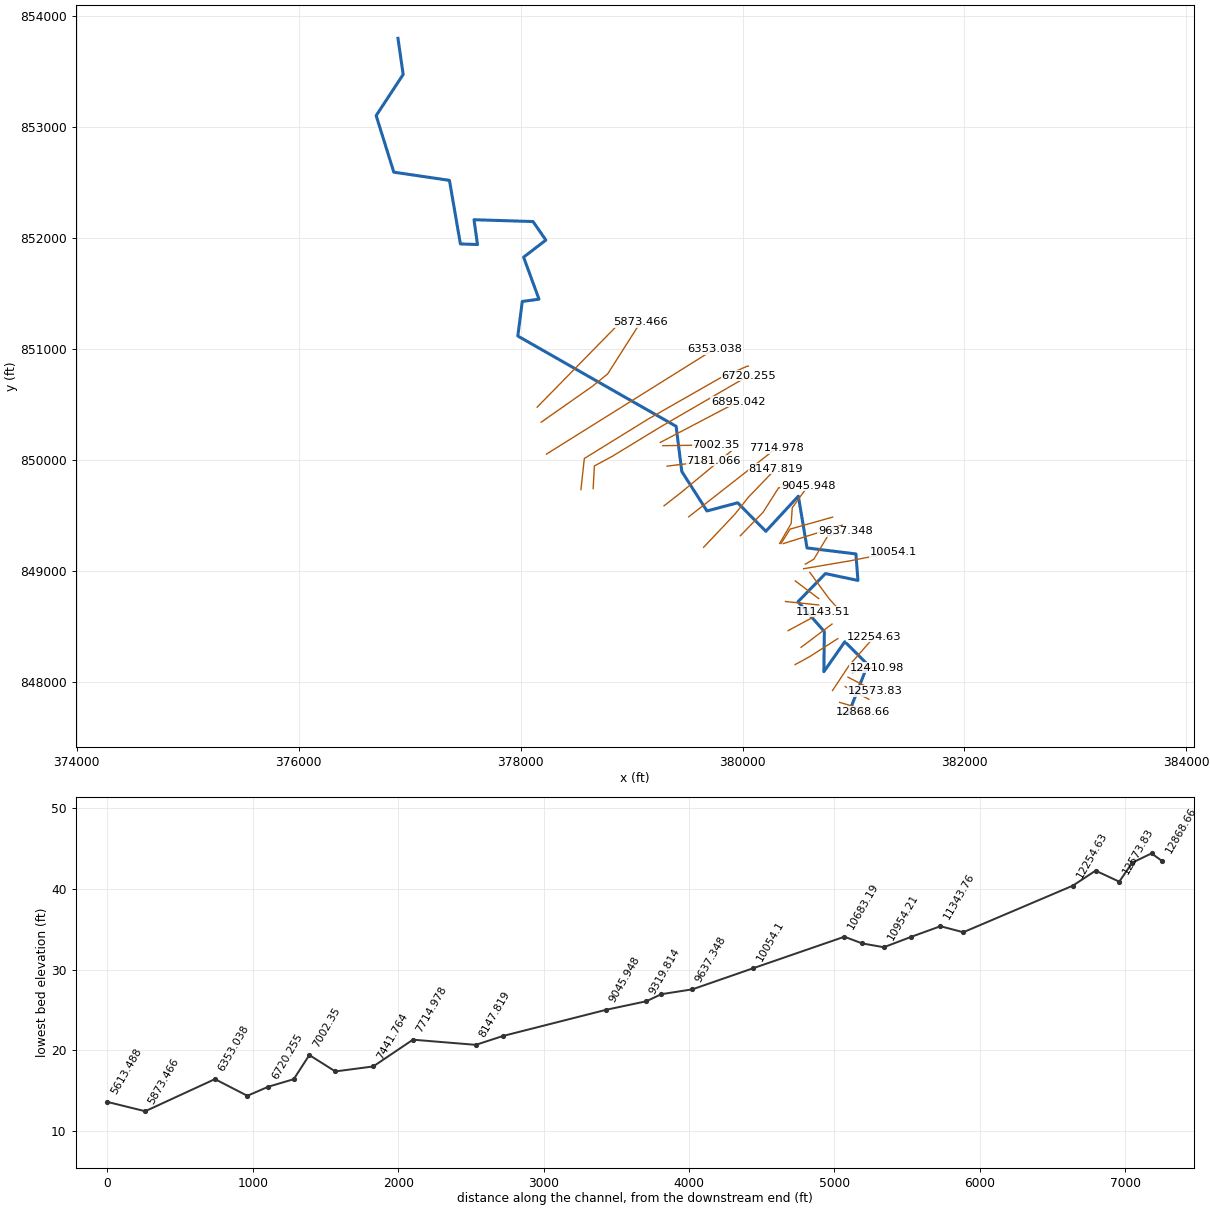
--- 6641_ras.prj (project) ---

Proj Title=6641
Current Plan=p01
Default Exp/Contr=0.3,0.1
English Units
Geom File=g01
Flow File=f01
Plan File=p01
Y Axis Title=Elevation
X Axis Title(PF)=Main Channel Distance
X Axis Title(XS)=Station
BEGIN DESCRIPTION:
RFD model 6641 exported to HEC-RAS
END DESCRIPTION:

--- 6641_ras.p01 (plan) ---

Plan Title=Plan 01
Program Version=4.10
Short Identifier=Plan 01
Geom File=g01
Flow File=f01
Subcritical Flow
Calc Critical at every XS
Secant Critical Depth

--- 6641_ras.f01 (steady flow) ---

Flow Title=Flow 01
Program Version=5.01
Number of Profiles= 6
Profile Names=10yr,25yr,50yr,100yr,100plus,500yr
River Rch & RM=6641,37,12868.66
 1862.94 3124.68 4359.33    5536 8082.57 10433.1
River Rch & RM=6641,37,12663.54
 1863.63 3125.91  4361.1 5538.32 8085.9510437.12
River Rch & RM=6641,37,12573.83
 1864.85 3128.05  4364.2 5542.37 8091.8710444.16
River Rch & RM=6641,37,12410.98
 1867.23  3132.3 4370.35 5550.43 8103.6310458.24
River Rch & RM=6641,37,12254.63
 1868.25 3134.11 4372.98 5553.88 8108.6610464.27
River Rch & RM=6641,37,11500.84
 1870.45 3138.03 4378.66 5561.34 8119.5510477.33
River Rch & RM=6641,37,11343.76
 1871.12 3139.23  4380.4 5563.62 8122.8910481.34
River Rch & RM=6641,37,11143.51
 1879.91  3154.9 4403.11 5593.43  8166.410533.51
River Rch & RM=6641,37,10954.21
 1883.57 3161.44 4412.63 5605.95 8184.6910555.55
River Rch & RM=6641,37,10805.63
 1884.23 3162.63 4414.36 5608.23 8188.0110559.56
River Rch & RM=6641,37,10683.19
 1885.56 3165.01 4417.82 5612.78 8194.6610567.57
River Rch & RM=6641,37, 10054.1
 1896.05 3183.68 4444.89 5648.27 8246.4810629.56
River Rch & RM=6641,37,9637.348
  1900.4 3191.46 4456.17  5663.1 8268.1310655.51
River Rch & RM=6641,37,9423.935
 1902.89 3195.91 4462.65 5671.62 8280.5610670.47
River Rch & RM=6641,37,9319.814
 1905.65 3200.89 4469.91  5681.2 8294.5510687.42
River Rch & RM=6641,37,8333.543
 1912.15  3212.6 4486.99 5703.74 8327.4610727.25
River Rch & RM=6641,37,8147.819
 1913.64 3215.26 4490.87 5708.83  8334.910736.21
River Rch & RM=6641,37,7714.978
 1916.39 3220.22 4498.11  5718.4 8348.8610753.11
River Rch & RM=6641,37,7441.764
 1924.26 3234.44 4518.89 5745.86 8388.9610801.78
River Rch & RM=6641,37,7181.066
 1983.06 3339.43 4671.33 5946.12 8681.3311150.89
River Rch & RM=6641,37, 7002.35
 1985.93 3344.61  4678.9 5956.13 8695.9511168.53
River Rch & RM=6641,37,6720.255
 1987.04 3346.62 4681.84 5960.01 8701.6211175.39
River Rch & RM=6641,37, 6575.77
 1992.25 3356.06 4695.66 5978.29 8728.3111207.68
River Rch & RM=6641,37,6353.038
 1993.99  3359.2 4700.26 5984.38  8737.211218.44
River Rch & RM=6641,37,5873.466
 2017.15 3401.14 4761.67 6065.63 8855.8211361.81
River Rch & RM=6641,37,5613.488
 2019.34 3405.11 4767.49 6073.34 8867.0711375.43
River Rch & RM=6641,37,5409.581
 2020.43  3407.1  4770.4 6077.19  8872.711382.24
River Rch & RM=6641,37, 5100.45
 2380.89  4046.6 5695.74 7289.3210642.4113440.78
River Rch & RM=6641,37,4736.966
 2384.18 4052.57  5704.5 7300.9310659.3613460.81
River Rch & RM=6641,37,4142.045
 2392.64 4067.96 5727.11 7330.9410703.1713512.65
River Rch & RM=6641,37, 3653.27
 2395.76 4073.63 5735.43 7341.99 10719.313531.73
River Rch & RM=6641,37,2180.357
 2420.34 4118.34 5801.12 7429.1710846.5813682.19
River Rch & RM=6641,37,1088.928
 2482.57 4232.16 5968.89 7652.4811172.6214068.96
River Rch & RM=6641,37, -0.2157
 2496.57 4257.75  6006.6 7702.6611245.8814155.63
Boundary for River Rch & Prof#=6641,37,1
Up Type= 0
Dn Type= 2
Boundary for River Rch & Prof#=6641,37,2
Up Type= 0
Dn Type= 2
Boundary for River Rch & Prof#=6641,37,2
Up Type= 0
Dn Type= 2
Boundary for River Rch & Prof#=6641,37,2
Up Type= 0
Dn Type= 2
Boundary for River Rch & Prof#=6641,37,2
Up Type= 0
Dn Type= 2
Boundary for River Rch & Prof#=6641,37,2
Up Type= 0
Dn Type= 2

--- 6641_ras.g01 (geometry) ---

Geom Title=6641
Program Version=4.10

River Reach=6641,37
Reach XY= 30
 380956.75776197 847716.30506511381129.283803642848154.673120648
380922.035539746 848360.83631511380733.233456418848090.654023424
380737.573734209848453.067217872380499.943525851848721.079370648
380747.339359209848974.985620663381040.308109283848913.136662319
381021.861928731849151.851940095380581.323734209849206.105412349
380503.198734194849672.685273424380210.229984194849355.844995648
379956.323734209849613.006453991 379679.63102594849539.221731767
 379452.85151197849895.124509558 379401.85324809  850302.0255512
377974.986928657851115.827634558378015.134498134851427.242565125
378165.959150866851447.858884558 378027.07026197851826.548120663
378227.808109209851980.627981752378111.705678731 852147.72867623
377580.021650881852164.004717872377611.488664746851940.480412319
377457.408803791851945.905759558377358.667484343 852518.82242623
376857.365400851852592.607148424376698.294220313853102.372773424
376941.783803642853473.466523424376894.779364333853798.801281899

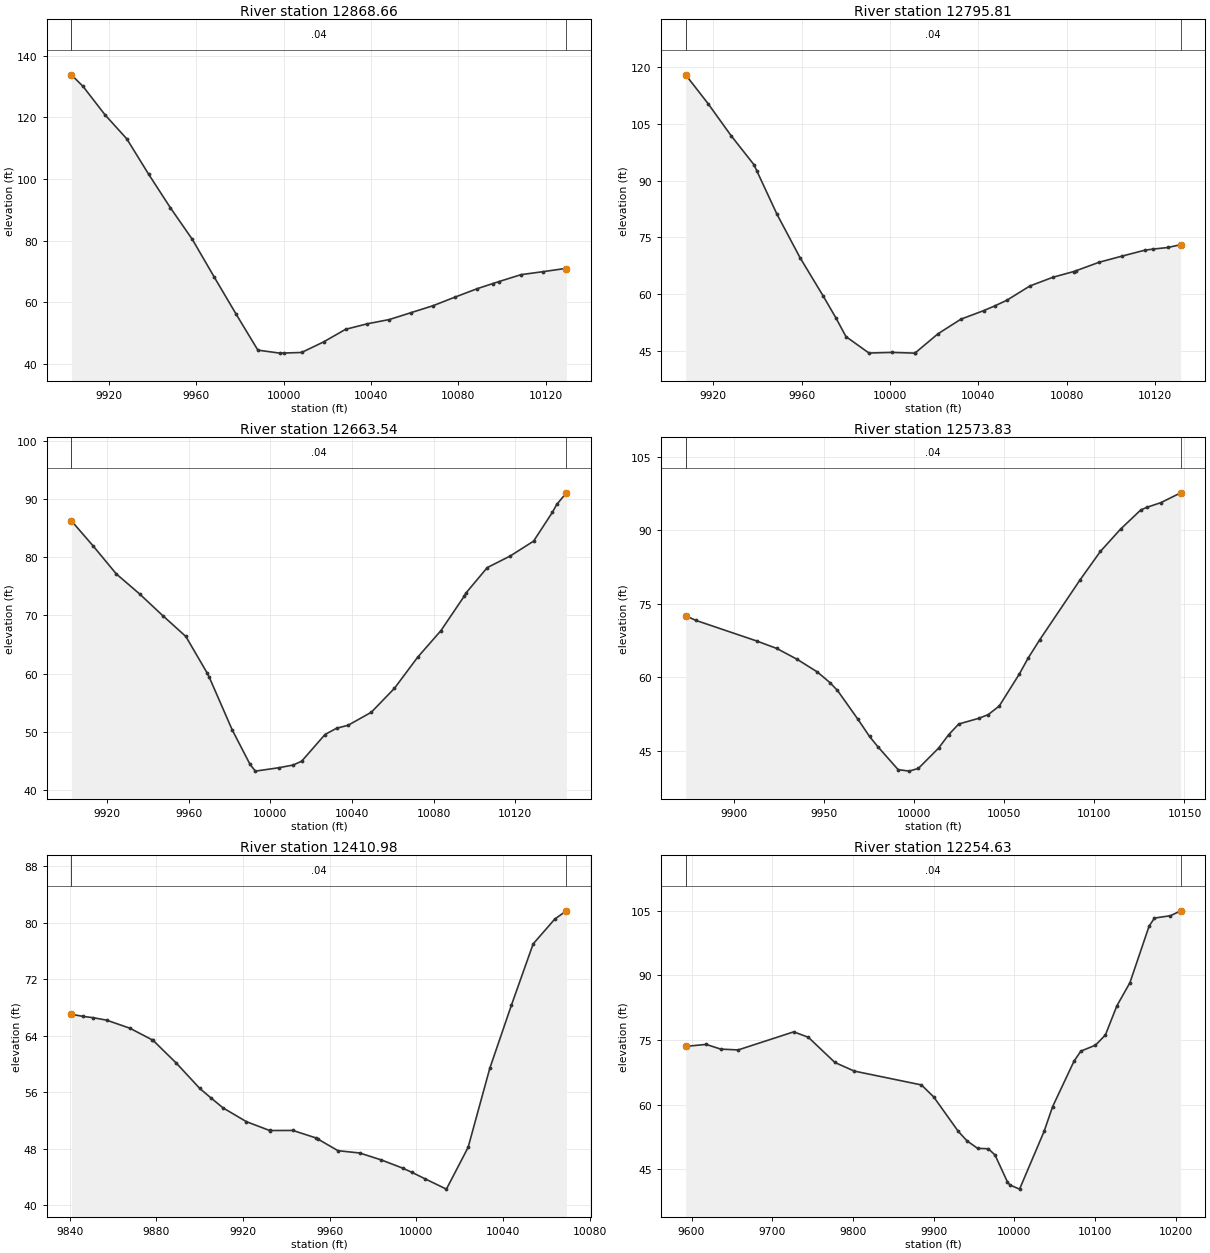
Type RM Length L Ch R = 1 ,12868.66,72.846400,72.846400,72.846400
XS GIS Cut Line= 3
380859.661396463847715.023656518380956.757761973847716.305065122
381085.699907398847728.051913837
#Sta/Elev= 27
9902.895133.80479908.234130.03739918.235120.85369928.236113.02959938.237101.5466
9948.23890.607329958.23980.385849968.23968.18602 9978.2456.173149988.24144.42975
9998.242 43.4565   1000043.4847410008.2843.6725910018.3247.0919210028.3651.17665
 10038.452.9923310048.4454.3647210058.4856.6248410068.5258.8739610078.5761.66658
10088.6164.3679610095.8466.0565710098.6566.6963110108.6968.9290910118.7369.89862
10128.7770.9160610129.4870.91945
#Mann= 3 , 0 , 0
9902.895    0.04       09902.895    0.04       010129.48    0.04       0
#XS Ineff= 2 , 0
       0                               0
Bank Sta=9902.895,10129.48
Exp/Cntr=0.3,0.1

Type RM Length L Ch R = 1 ,12795.81,132.268700,132.268700,132.268700
XS GIS Cut Line= 2
380875.280232385847813.999487907381090.558010161847751.499487907
#Sta/Elev= 29
9907.449117.9535 9917.57110.36759927.983101.90889938.39694.192369939.727 92.5086
9948.80981.104889959.22269.654719969.63459.592889975.59453.606139980.04748.76635
 9990.4644.4269410000.8744.5880510011.2944.3979510011.4644.48391 10021.749.50132
10032.1153.3749310042.5255.6548310047.3356.8495110052.9458.3845710063.3562.14913
10073.7664.4508310083.1965.9630310084.1866.1609710094.5968.39558   1010570.03184
10115.4271.6136610119.0671.8886410125.83 72.317210131.6273.06925
#Mann= 3 , 0 , 0
9907.449    0.04       09907.449    0.04       010131.62    0.04       0
#XS Ineff= 2 , 0
       0                               0
Bank Sta=9907.449,10131.62
Exp/Cntr=0.3,0.1

Type RM Length L Ch R = 1 ,12663.54,89.708600,89.708600,89.708600
XS GIS Cut Line= 2
380925.627454594847956.360599026381139.169121265847841.777265683
#Sta/Elev= 29
9902.64986.240449913.28581.928029924.63477.121969935.98373.701759947.33169.97431
 9958.6866.378879968.97660.183119970.02959.463329981.37750.334719990.12644.40014
9992.72643.2546410004.0743.8305110011.2844.3066310015.4244.9748210026.7749.53371
10032.4350.6164810038.1251.1332910049.4753.3679610060.8257.4881910072.1762.82296
10083.5267.3696910094.86 73.251110095.87 73.870610106.2178.2035510117.5680.22185
10128.9182.7528610138.1787.7314710140.2689.0643210144.99  91.051
#Mann= 3 , 0 , 0
9902.649    0.04       09902.649    0.04       010144.99    0.04       0
#XS Ineff= 2 , 0
       0                               0
Bank Sta=9902.649,10144.99
Exp/Cntr=0.3,0.1

Type RM Length L Ch R = 1 ,12573.83,162.855900,162.855900,162.855900
XS GIS Cut Line= 2
380949.933010146848041.430043444381194.724676818847916.430043444
#Sta/Elev= 30
9873.01672.566239878.70571.62698 9912.3967.436529923.619 65.90459934.847 63.7063
9946.07561.132239953.12158.948259957.30457.352069968.53251.54849 9975.1147.97188
 9979.7645.874579990.98941.208969997.09940.8999810002.2241.4485210013.45 45.5855
10019.0948.3416910024.6750.50884 10035.951.6769210041.0852.4352510047.13 54.1656
10058.3660.7340810063.0763.8708310069.5967.6566510092.0479.9023910103.2785.67132
 10114.590.2311910125.7394.1394710129.0394.6587110136.96   95.6410147.8897.62884
#Mann= 3 , 0 , 0
9873.016    0.04       09873.016    0.04       010147.88    0.04       0
#XS Ineff= 2 , 0
       0                               0
Bank Sta=9873.016,10147.88
Exp/Cntr=0.3,0.1

Type RM Length L Ch R = 1 ,12410.98,156.346700,156.346700,156.346700
XS GIS Cut Line= 3
380989.863565728848081.360599026381095.766343489848123.027265683
381210.349676833848128.235599026
#Sta/Elev= 30
9840.82867.036129846.34766.734169850.76866.561449857.09466.20838 9867.84 65.0618
9878.08163.422199878.58663.325789889.332 60.09649900.078 56.53039905.39455.15057
9910.82453.77592 9921.5751.827959932.31750.572449932.70750.567679943.06350.57887
9953.80949.508789954.63249.355879963.87647.708819973.88647.384779983.89646.39775
9993.90745.218999998.07744.6312510003.9243.7467210013.9342.2620810023.9448.17239
10033.9559.3773110043.9668.3494510053.9777.0136410063.9880.5410710069.3381.70169
#Mann= 3 , 0 , 0
9840.828    0.04       09840.828    0.04       010069.33    0.04       0
#XS Ineff= 2 , 0
       0                               0
Bank Sta=9840.828,10069.33
Exp/Cntr=0.3,0.1

Type RM Length L Ch R = 1 ,12254.63,753.795400,753.795400,753.795400
XS GIS Cut Line= 3
380810.961708587847920.792462687380959.365018627848144.616206263
381186.395615756 848404.52464767
#Sta/Elev= 30
9592.74673.52115 9618.15 73.98559636.24672.892639657.78672.702159726.72776.90028
9744.82375.63806 9777.7769.790679801.76767.795129885.06564.581989900.26561.79638
9930.66753.823029941.47551.618749954.75349.861919968.03149.774919976.26948.32296
 9991.4742.156259994.586 41.381510006.6740.4073910037.0753.79419 10047.759.56739
10074.2570.1163510082.6772.4229710100.8173.8124110113.0776.1682610127.3682.95499
10143.48 88.2964 10167.2101.395410173.88103.294310193.75103.8418 10206.4104.9753
#Mann= 3 , 0 , 0
9592.746    0.04       09592.746    0.04       0 10206.4    0.04       0
#XS Ineff= 2 , 0
       0                               0
Bank Sta=9592.746,10206.4
Exp/Cntr=0.3,0.1

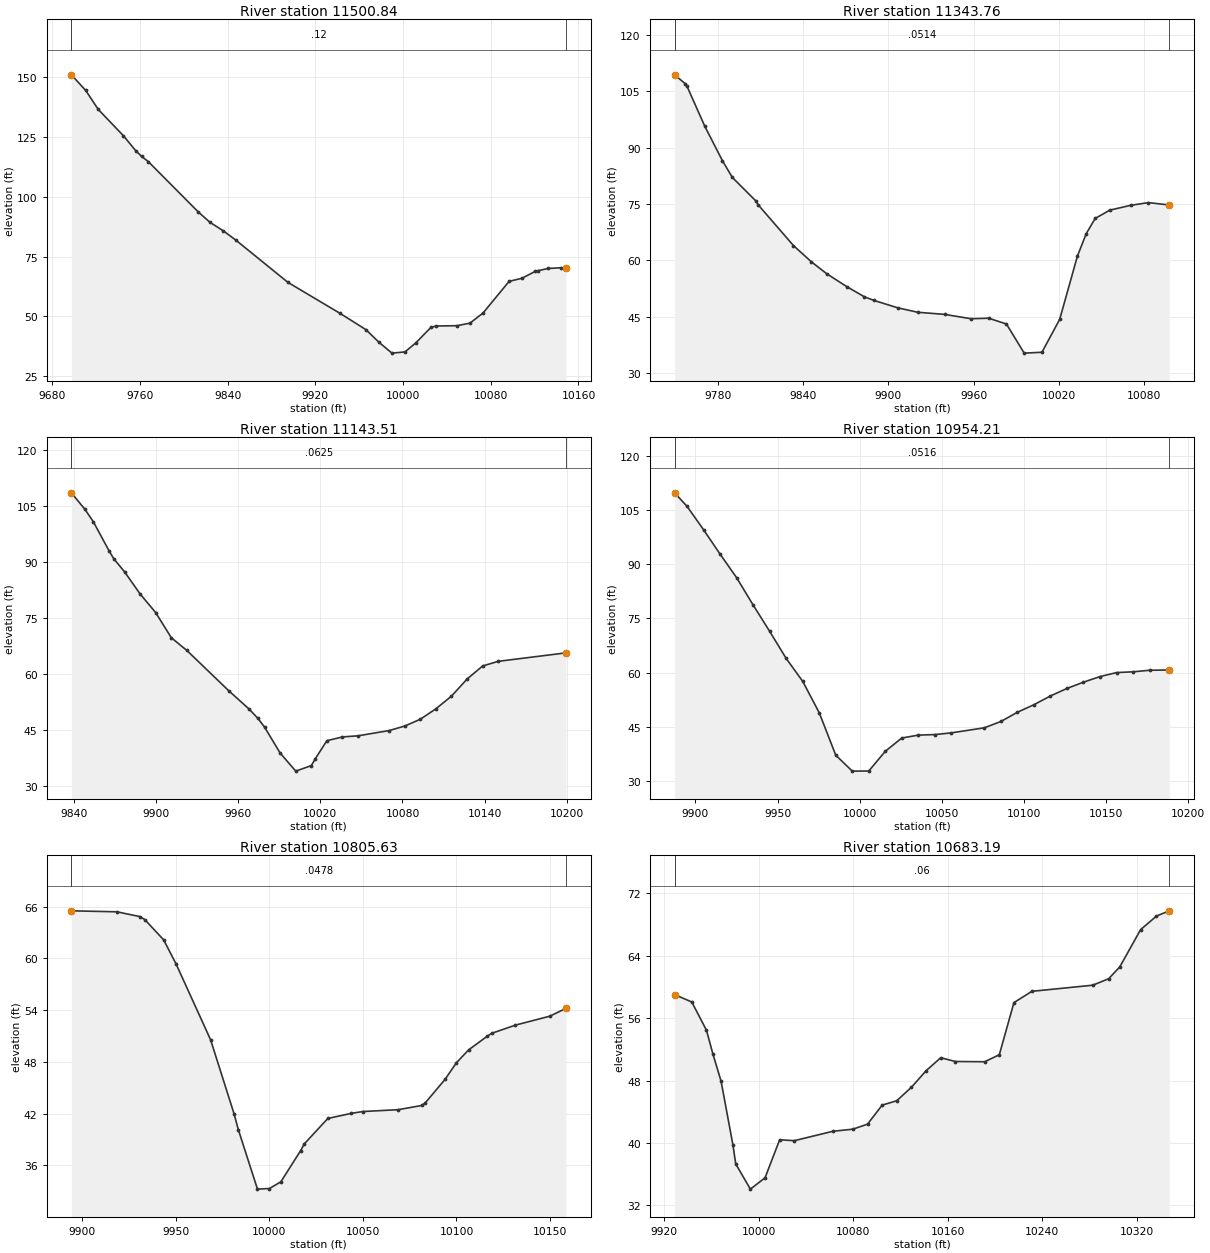
Type RM Length L Ch R = 1 ,11500.84,157.076600,157.076600,157.076600
XS GIS Cut Line= 3
 380473.55394772848154.173057148 380604.98598617848226.386192555
380858.730917115848388.741995803
#Sta/Elev= 30
9697.419151.00199710.479144.47549721.889136.55449744.709125.61089756.119119.2754
9761.436116.91059767.529114.73769813.168 93.67439823.73789.362189835.98885.78028
9847.39981.902549894.88664.240789942.37351.298299966.11744.455749977.98939.17412
9989.86134.6379610001.7335.13762 10011.839.0099310025.4845.4375810030.3545.98517
10049.2246.1050310061.0947.1973610072.9651.4213710096.7164.6440810108.5865.96615
10120.4568.8102310123.1369.1142710132.3270.0258310144.1970.3424110148.6270.04159
#Mann= 3 , 0 , 0
9697.419    0.12       09697.419    0.12       010148.62    0.12       0
#XS Ineff= 2 , 0
       0                               0
Bank Sta=9697.419,10148.62
Exp/Cntr=0.3,0.1

Type RM Length L Ch R = 1 ,11343.76,200.246300,200.246300,200.246300
XS GIS Cut Line= 2
380528.058010146848310.527265668380806.703843489848520.162682354
#Sta/Elev= 30
9749.261109.31119756.701106.97139757.948106.31439770.46295.711039782.97686.48849
9789.96882.049739806.60175.790269808.00474.851319833.03263.961679845.546 59.6812
9856.50256.476619870.57453.060839883.08950.343199889.76949.387869906.40347.43909
9920.63146.23997 9939.6745.674979958.17344.519159970.68744.657059983.20143.11997
9995.71535.3831410008.2335.6151710020.7444.3516310033.2661.1752510039.4767.13752
10045.7771.16234 10056.173.36982 10070.874.6459110083.3175.3636110097.9674.74043
#Mann= 3 , 0 , 0
9749.261  0.0514       09749.261  0.0514       010097.96  0.0514       0
#XS Ineff= 2 , 0
       0                               0
Bank Sta=9749.261,10097.96
Exp/Cntr=0.3,0.1

Type RM Length L Ch R = 1 ,11143.51,189.304400,189.304400,189.304400
XS GIS Cut Line= 2
380410.870510161848460.266849026380728.578843504848632.141849011
#Sta/Elev= 30
9838.207108.44039848.155103.99839854.272100.68529865.64192.993889869.17190.81617
9877.01187.340769888.38181.42273 9899.7576.445929911.20469.709729922.48966.33804
9953.23755.516359967.96750.671239974.25348.245759979.33745.801259990.70638.88085
10002.0834.0739410013.4535.5573410016.2937.3590310024.8142.2047810036.1843.21625
10047.5543.5105910070.2944.9147310081.6646.1229210093.03 47.9357 10104.450.72746
10115.7754.1007610127.1458.6648210138.51 62.165910149.8863.4088310199.4365.67721
#Mann= 3 , 0 , 0
9838.207  0.0625       09838.207  0.0625       010199.43  0.0625       0
#XS Ineff= 2 , 0
       0                               0
Bank Sta=9838.207,10199.43
Exp/Cntr=0.3,0.1

Type RM Length L Ch R = 1 ,10954.21,148.574900,148.574900,148.574900
XS GIS Cut Line= 2
380387.433010161 848723.28768234380686.912176818 848692.03768234
#Sta/Elev= 30
9887.299109.70269894.908105.94549904.96299.471359915.016 92.7464 9925.0786.22693
9935.12578.678689945.17971.415899955.233  63.9179965.28857.595249975.34248.91831
9985.39637.193319995.45132.78259 10005.532.8154910015.5638.2711910025.6141.93236
10035.67 42.740210045.7242.8803310055.7843.3624710075.8844.7582710085.9446.50798
10095.99  49.05610106.0551.14213 10116.153.5579910126.1655.6339710136.21 57.3708
10146.2658.9114810156.3260.0183410166.3760.2336110176.4360.66118 10188.460.74109
#Mann= 3 , 0 , 0
9887.299  0.0516       09887.299  0.0516       0 10188.4  0.0516       0
#XS Ineff= 2 , 0
       0                               0
Bank Sta=9887.299,10188.4
Exp/Cntr=0.3,0.1

Type RM Length L Ch R = 1 ,10805.63,122.439200,122.439200,122.439200
XS GIS Cut Line= 2
380475.641922206848908.617543444380686.579422206848749.763376802
#Sta/Elev= 28
 9894.4265.501399918.65365.389189931.17264.823899933.67964.46858 9943.6962.13371
9950.30259.346839968.72850.564959981.24641.992429983.54840.142619993.76533.25453
10000.1733.3259310006.2834.1106810016.7937.70873 10018.838.5056210031.3241.44213
10043.8442.0335310050.0442.2473910068.8842.4582210081.3942.9454710083.2943.23729
10093.9145.9705610099.9147.8783410106.4349.3798110116.5350.9891910118.9551.31938
10131.4752.2576410149.7853.2900110158.4854.19996
#Mann= 3 , 0 , 0
 9894.42  0.0478       0 9894.42  0.0478       010158.48  0.0478       0
#XS Ineff= 2 , 0
       0                               0
Bank Sta=9894.42,10158.48
Exp/Cntr=0.3,0.1

Type RM Length L Ch R = 1 ,10683.19,629.092600,629.092600,629.092600
XS GIS Cut Line= 3
380605.850255543848986.742543435380781.079929989 848747.47773939
380863.101400632 848657.01392077
#Sta/Elev= 30
9928.94759.018039943.50258.065489955.89754.450229961.357 51.40849968.29247.90896
9978.28239.768349980.68737.315629993.08234.0835710005.4835.5329110017.8740.40979
10030.2740.29275 10062.9 41.497710079.8541.7681810092.2442.4094610104.6444.85059
10117.0345.4148510129.4347.1423410141.8249.2558410154.2250.9237510166.6150.44045
 10191.450.40896 10203.851.3044810216.1957.9888210231.3559.4347510282.8560.21777
10296.3561.0449610305.7962.5658910323.3567.3283210336.8569.0785410347.6369.75133
#Mann= 3 , 0 , 0
9928.947    0.06       09928.947    0.06       010347.63    0.06       0
#XS Ineff= 2 , 0
       0                               0
Bank Sta=9928.947,10347.63
Exp/Cntr=0.3,0.1

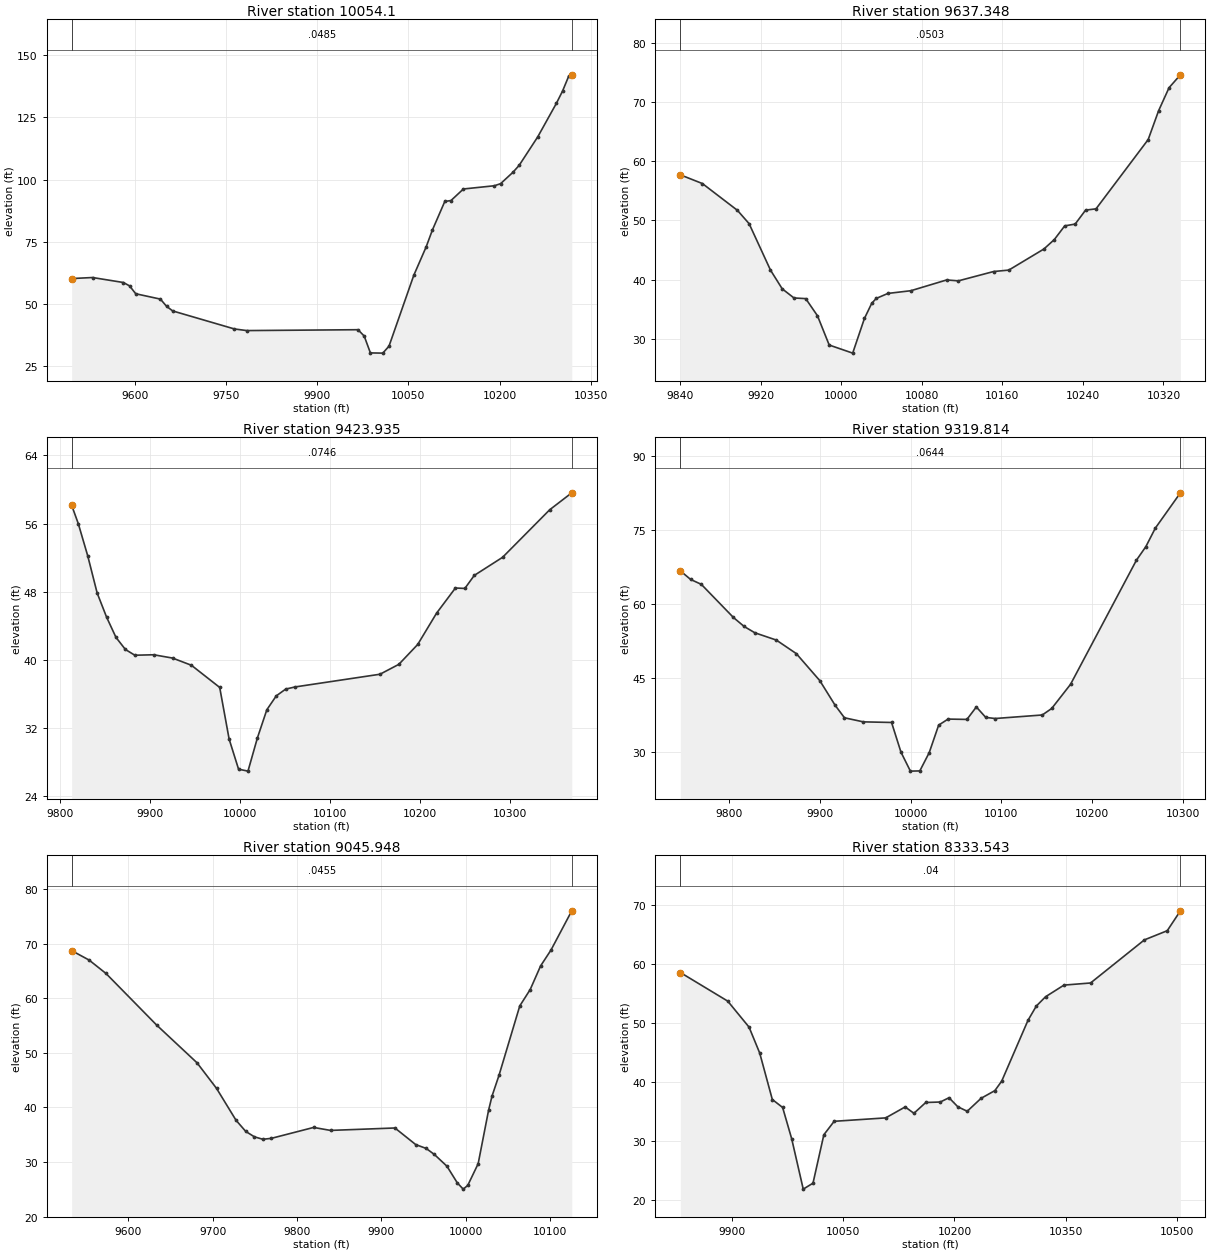
Type RM Length L Ch R = 1 , 10054.1,416.753600,416.753600,416.753600
XS GIS Cut Line= 3
 380551.16275552849018.860599028380960.884977756849088.305043492
381359.790933021849166.838577817
#Sta/Elev= 30
9496.53760.173179530.85760.58517 9581.5758.582279591.71357.225559601.85554.05517
9642.426  51.9039652.56948.998429662.71147.135919764.13739.891449784.42339.24371
9967.25739.594119977.44937.046999987.64130.2640110008.0230.1737410018.2232.97836
10058.9861.4887610079.37 72.944510089.5679.6944510109.94 91.176410120.1491.55668
10140.5296.1996210191.4897.5022210201.6798.3410910222.06102.937710232.25105.7267
10262.82117.1951 10293.4 130.65910303.59135.620110313.78141.655610318.67142.1209
#Mann= 3 , 0 , 0
9496.537  0.0485       09496.537  0.0485       010318.67  0.0485       0
#XS Ineff= 2 , 0
       0                               0
Bank Sta=9496.537,10318.67
Exp/Cntr=0.3,0.1

Type RM Length L Ch R = 1 ,9637.348,213.412400,213.412400,213.412400
XS GIS Cut Line= 4
380566.099128866849059.692177369380643.313211197849105.000000017
380769.118237151849314.798352635380925.886371525849357.124305335
#Sta/Elev= 30
9840.36257.700189862.27656.22713 9897.0651.699719908.65449.448469929.88741.60079
9941.548 38.43189953.20836.893869964.86836.781259976.52833.887799988.18828.93862
10011.5127.5714410023.1733.4327310030.3935.9825710034.8336.8086610046.4937.65956
10069.2838.1184810104.7939.9367210116.4539.7855410151.4341.3621110166.5141.60291
10201.3245.1613810211.6846.7566110222.0449.07749 10232.449.3779910242.7551.73804
10253.1151.95369 10304.963.6598510315.2668.5383410325.6272.42578 10336.974.59965
#Mann= 3 , 0 , 0
9840.362  0.0503       09840.362  0.0503       0 10336.9  0.0503       0
#XS Ineff= 2 , 0
       0                               0
Bank Sta=9840.362,10336.9
Exp/Cntr=0.3,0.1

Type RM Length L Ch R = 1 ,9423.935,104.121400,104.121400,104.121400
XS GIS Cut Line= 2
 380368.00303331849245.423099011380898.384977758849411.221710116
#Sta/Elev= 30
9813.30158.149969820.632 56.00629831.10952.237029841.58647.871729852.06445.04182
9862.54142.655649873.01841.237659883.49540.56365 9904.4540.618849925.40440.23061
9946.35939.38717 9977.7936.786959988.26730.724169998.74527.1975710009.2226.96865
 10019.730.8695510030.18 34.168810040.6535.7964110051.1336.5921410061.6136.84468
 10155.938.3345610176.8639.4947510197.8141.8262610218.7745.4977610239.7248.44878
 10250.248.3993310260.6749.9274210292.1152.0493110344.4957.6293710368.9959.61446
#Mann= 3 , 0 , 0
9813.301  0.0746       09813.301  0.0746       010368.99  0.0746       0
#XS Ineff= 2 , 0
       0                               0
Bank Sta=9813.301,10368.99
Exp/Cntr=0.3,0.1

Type RM Length L Ch R = 1 ,9319.814,273.866200,273.866200,273.866200
XS GIS Cut Line= 3
380346.808010161849245.423099011380428.839260146 849375.63143234
380811.651760146849483.704349011
#Sta/Elev= 30
9745.848 66.75829757.16765.009819768.98664.013559804.44357.280049816.26255.45743
9828.08154.175639851.71952.699549873.77949.951849899.74244.455679916.53439.48528
9926.92536.919569947.70736.093289978.87935.97021 9989.2729.938879999.66126.09097
10010.0526.1366910020.4429.8551910030.8335.4293210041.2236.6575910062.0136.58936
 10072.439.1189110082.7936.9944310093.1836.7739510145.13 37.488510155.5238.81017
10176.31 43.711410249.0468.9264810259.4371.6756210269.8275.4130910297.5282.59035
#Mann= 3 , 0 , 0
9745.848  0.0644       09745.848  0.0644       010297.52  0.0644       0
#XS Ineff= 2 , 0
       0                               0
Bank Sta=9745.848,10297.52
Exp/Cntr=0.3,0.1

Type RM Length L Ch R = 1 ,9045.948,712.404300,712.404300,712.404300
XS GIS Cut Line= 4
 380334.65523237849246.291154578380438.821899056849426.846710131
380448.370510146849568.339765683380590.297593489849764.954349026
#Sta/Elev= 30
9532.79968.70597  9553.566.975289573.51164.519799633.544 55.07629681.39148.16967
9704.481 43.49689727.57137.663379739.116 35.6113 9749.4234.618039759.442 34.1716
9769.46534.340929819.57936.338749839.62435.794459915.94336.238839940.60933.19817
9952.94332.499559962.73131.389029977.60929.241719989.94226.177639996.90225.04582
10002.2825.7286510014.6129.7001710026.9439.4712310031.0742.0929210039.2745.85815
10063.9458.5871910076.2761.5782910088.61 65.904210100.9468.8152710125.55 75.9922
#Mann= 3 , 0 , 0
9532.799  0.0455       09532.799  0.0455       010125.55  0.0455       0
#XS Ineff= 2 , 0
       0                               0
Bank Sta=9532.799,10125.55
Exp/Cntr=0.3,0.1

Type RM Length L Ch R = 1 ,8333.543,185.724300,185.724300,185.724300
XS GIS Cut Line= 4
379980.488565713849315.735599011380185.349676818849527.541154578
380324.238565713849746.291154563 380442.29412128849774.068932354
#Sta/Elev= 30
 9830.0358.537449894.05453.680169922.82249.268829937.20644.871059954.217 36.9937
9968.12935.645349980.35730.334189995.95321.7923710009.1322.8039110023.7831.01445
10037.6933.2974510107.2533.8762310133.53 35.733510145.3834.6548710161.3636.48913
10180.9236.5697410192.7637.2941810204.6135.7619510217.3335.0003810235.9837.19431
10254.6438.5032810263.8340.1035710299.3750.4306110310.6152.8492210323.0654.42456
10347.9256.4003210383.8256.7591710456.5164.0730910487.3365.62633 10505.168.99908
#Mann= 3 , 0 , 0
 9830.03    0.04       0 9830.03    0.04       0 10505.1    0.04       0
#XS Ineff= 2 , 0
       0                10190.45       0
Bank Sta=9830.03,10505.1
Exp/Cntr=0.3,0.1

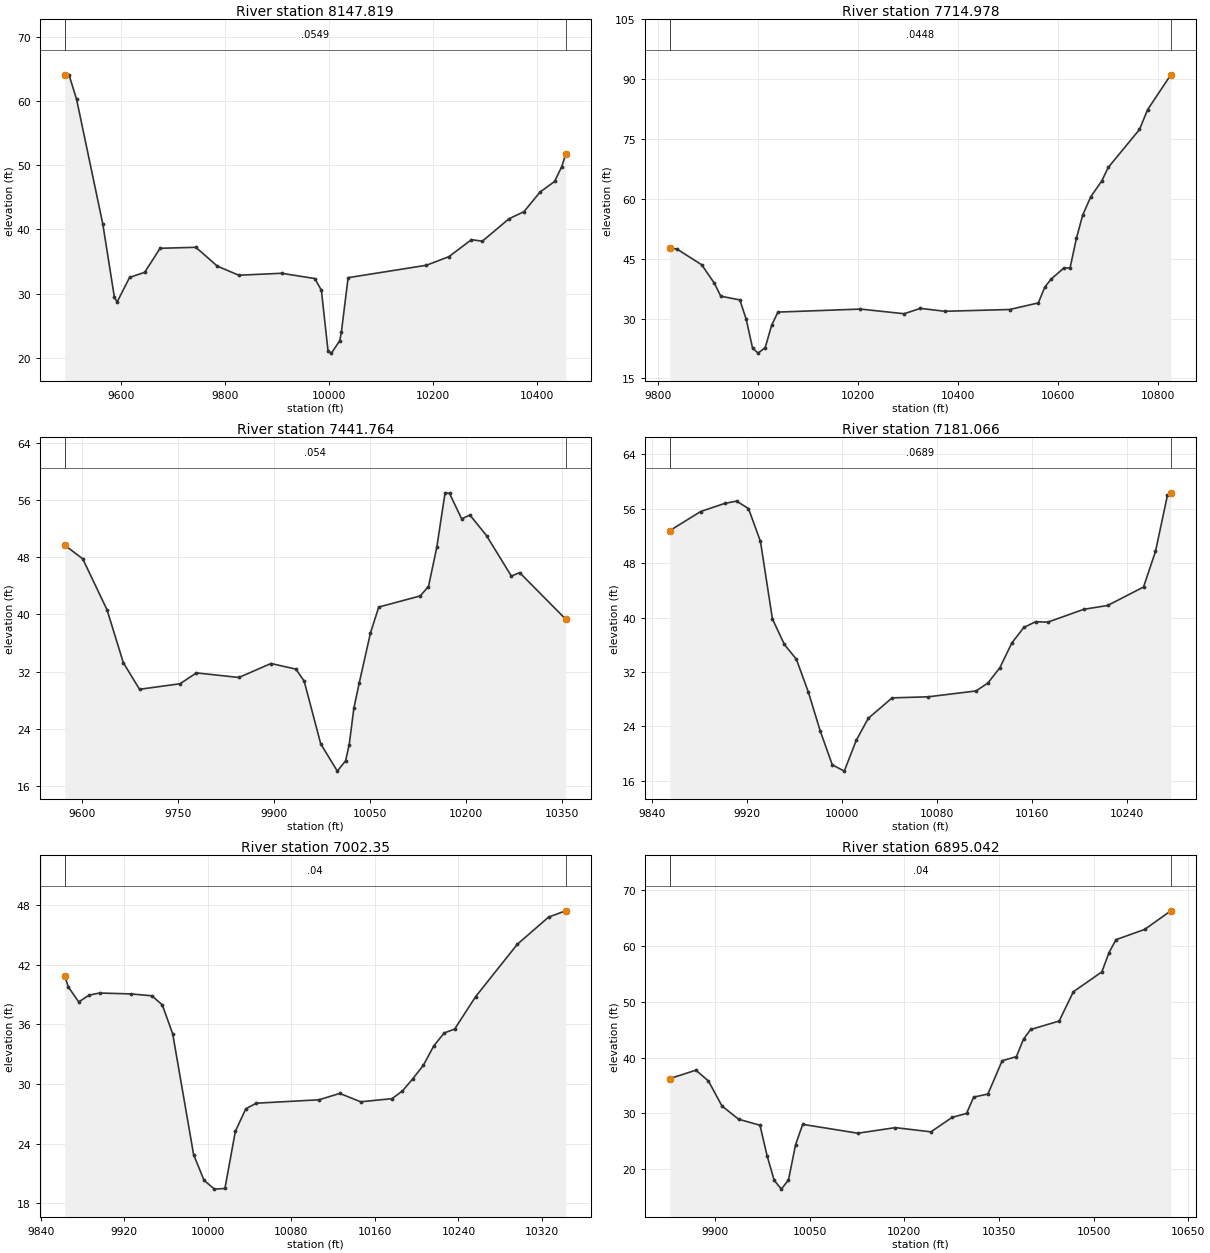
Type RM Length L Ch R = 1 ,8147.819,432.841000,432.841000,432.841000
XS GIS Cut Line= 4
379649.502002786849211.945223068379931.371088877849510.180043535
380053.766922197849663.825876805 380300.62199865849920.411520704
#Sta/Elev= 30
9491.57264.111519499.57664.142859514.13560.325949564.57340.850199586.92729.38896
9592.09228.683129616.04432.514459645.16133.32107 9674.6537.063219743.448 37.2199
9784.72734.277859826.00532.858819908.09333.162859972.01932.345419984.80430.51345
9997.58921.0050110004.0520.69838 10020.122.6406710023.1623.9393610036.1532.47833
10186.6934.4160310229.96 35.759810273.23 38.406210294.2738.1743210345.3541.66869
10374.1942.7839410405.2845.8508810433.0447.4943310446.9149.8318710454.4251.75017
#Mann= 3 , 0 , 0
9491.572  0.0549       09491.572  0.0549       010454.42  0.0549       0
#XS Ineff= 2 , 0
       09731.112        10154.16       0
Bank Sta=9491.572,10454.42
Exp/Cntr=0.3,0.1

Type RM Length L Ch R = 1 ,7714.978,273.214100,273.214100,273.214100
XS GIS Cut Line= 2
379514.990920495849486.402559863380303.615638905850103.614656066
#Sta/Elev= 30
9824.64647.657499838.59647.432349888.15143.483989913.54838.848349926.24635.61444
9964.34234.67929 9977.0429.859679989.73922.6450510000.8521.3365210015.1422.72885
10027.8328.2829410040.5331.6241510205.6132.38266 10292.931.2124210325.3532.56028
10374.0331.8286110503.8332.2727310561.1733.9231110573.8737.8070610586.5739.87827
10611.9742.6366710624.6742.7133910637.3650.1108810649.8655.9400510666.0860.54986
10688.1664.5294810700.8667.8772910763.4377.4028210779.6682.3656710826.0991.10968
#Mann= 3 , 0 , 0
9824.646  0.0448       09824.646  0.0448       010826.09  0.0448       0
#XS Ineff= 2 , 0
       09865.001        10415.96       0
Bank Sta=9824.646,10826.09
Exp/Cntr=0.3,0.1

Type RM Length L Ch R = 1 ,7441.764,260.697600,260.697600,260.697600
XS GIS Cut Line= 3
 379292.90931452849585.669120153379449.201744656849707.860709757
379900.521853352850080.792883454
#Sta/Elev= 30
9572.46749.713529600.50747.803499638.588 40.63919663.97433.246129689.361 29.5031
9752.82930.283119778.37731.804759844.85931.163619895.12733.122549934.04432.33848
9947.01630.661439972.96121.848979998.90518.0246210011.8819.4801710017.5521.75455
10024.8526.8694810033.2530.4117710050.7937.4064610063.7741.0412410128.6342.60313
 10141.643.9220810154.5749.4163710167.5457.0655610174.5456.9784210193.4953.41688
10206.4653.9479210232.4151.0650910271.3245.38598 10284.345.8704210356.32 39.3458
#Mann= 3 , 0 , 0
9572.467   0.054       09572.467   0.054       010356.32   0.054       0
#XS Ineff= 2 , 0
       09735.101        10098.88       0
Bank Sta=9572.467,10356.32
Exp/Cntr=0.3,0.1

Type RM Length L Ch R = 1 ,7181.066,178.716400,178.716400,178.716400
XS GIS Cut Line= 2
379319.391922206849943.166154563379737.794699982849993.513376802
#Sta/Elev= 30
9855.15452.791519880.94755.583929901.09256.772719911.16457.121579921.23656.02231
9931.30851.18744 9941.3839.787729951.45236.032999961.52433.864469971.59729.03869
9981.66923.278949991.741 18.340710001.8117.4074910011.8921.9278510021.9625.16573
 10042.128.1819310072.3228.3376410112.61 29.195310122.6830.3646510132.7532.62245
10142.8236.25906 10152.938.5381710162.9739.3890610173.0439.3141510203.2641.20277
 10223.441.7696810253.6244.4835310263.6949.7157810273.7657.9911210276.5858.33782
#Mann= 3 , 0 , 0
9855.154  0.0689       09855.154  0.0689       010276.58  0.0689       0
#XS Ineff= 2 , 0
       0                10206.06       0
Bank Sta=9855.154,10276.58
Exp/Cntr=0.3,0.1

Type RM Length L Ch R = 1 , 7002.35,107.307900,107.307900,107.307900
XS GIS Cut Line= 2
379281.703843504850127.599024937379761.304537952850134.109441608
#Sta/Elev= 30
9863.06140.842749866.35839.775039876.35938.257459886.35938.94718 9896.3639.15526
9926.36339.063929946.36538.877869956.36637.968579966.36735.050669986.36922.91776
 9996.37 20.319710006.3719.4360610016.3719.5017810026.3725.2512610036.37   27.51
10046.3728.0749710106.3828.4187810126.3829.0593810146.3828.2186810176.3928.53242
10186.3929.3087210196.3930.5483910206.3931.8835410216.3933.8423710226.39 35.1391
10236.3935.5353210256.3938.77945 10296.444.05934 10326.446.7933410342.7147.41937
#Mann= 3 , 0 , 0
9863.061    0.04       09863.061    0.04       010342.71    0.04       0
#XS Ineff= 2 , 0
       0                10202.26       0
Bank Sta=9863.061,10342.71
Exp/Cntr=0.3,0.1

Type RM Length L Ch R = 1 ,6895.042,174.787000,174.787000,174.787000
XS GIS Cut Line= 2
379258.628033308850156.707821231379961.792284231850525.321783596
#Sta/Elev= 30
9828.48736.238139869.55437.741719889.42335.812649910.96131.331039937.29828.95787
 9971.1727.884019982.46122.415689993.75218.0260610005.0416.4466210016.3318.07718
10027.6224.3961610038.9128.0443210126.3426.4559210185.6927.4571110242.1526.70323
10276.0229.30554 10298.629.9959210309.8932.9202910332.4733.4667810355.0639.42697
10377.6440.1672710388.9343.3018710400.2245.0239210445.3846.5380310467.9651.77935
10513.1355.3391210524.4258.7790110535.5761.1107610580.87 62.932810622.4166.26754
#Mann= 3 , 0 , 0
9828.487    0.04       09828.487    0.04       010622.41    0.04       0
#XS Ineff= 2 , 0
       0                10145.89       0
Bank Sta=9828.487,10622.41
Exp/Cntr=0.3,0.1

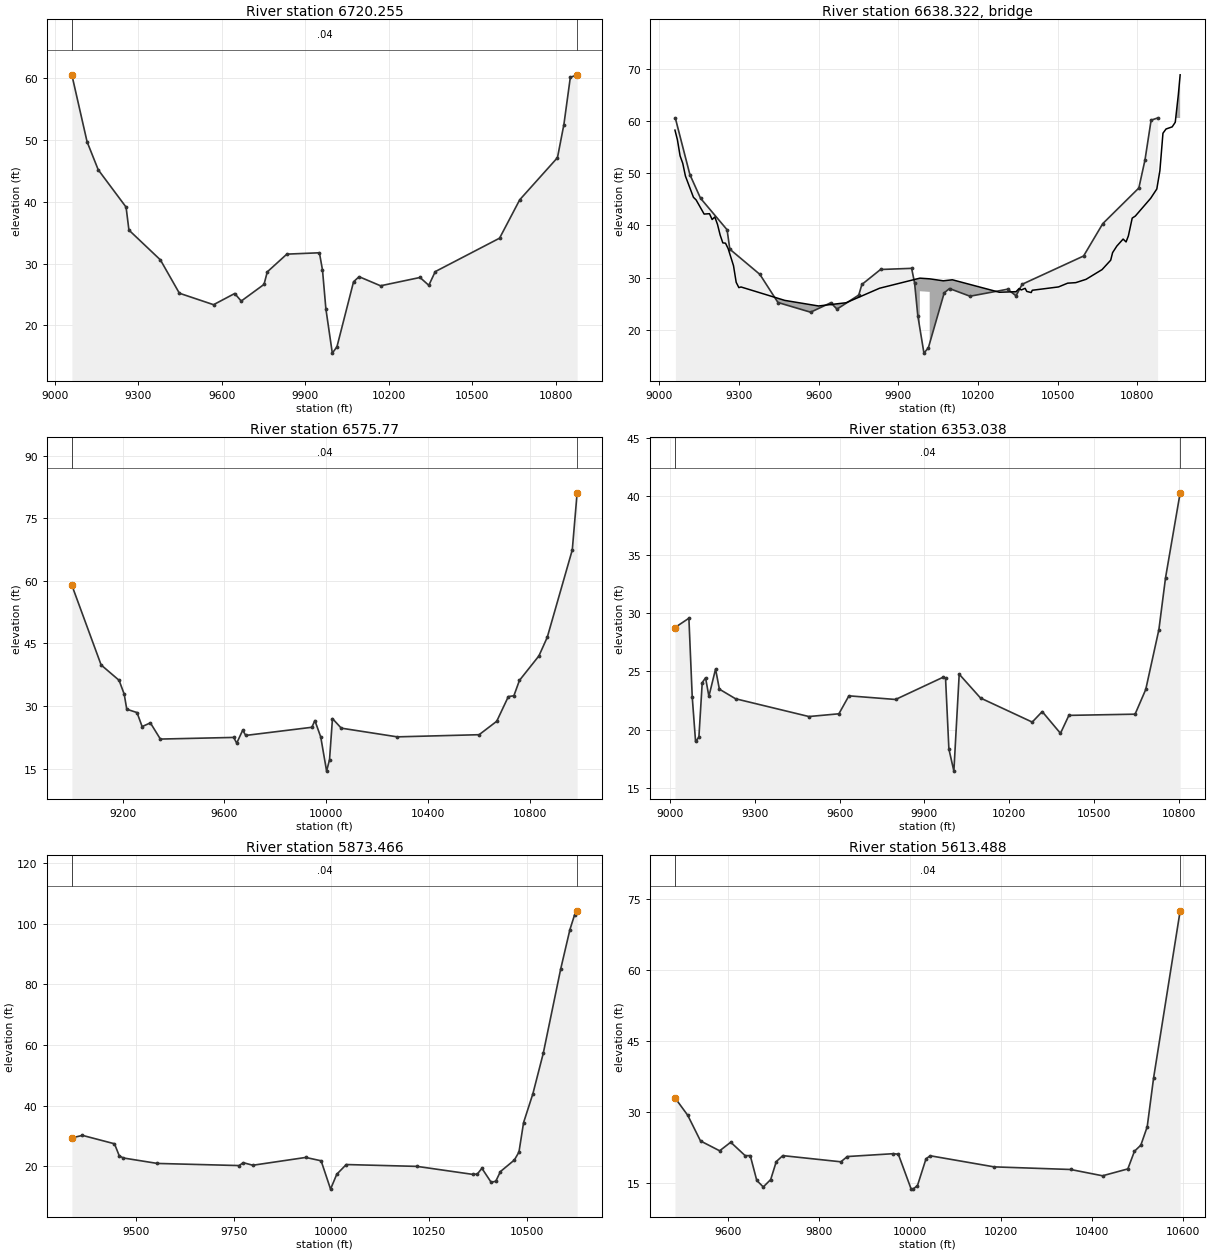
Type RM Length L Ch R = 1 ,6720.255,144.485500,144.485500,144.485500
XS GIS Cut Line= 5
378653.856082946849740.612585559378665.340756655849945.228286877
378830.071360737850034.015363336 379264.48378104850298.918830901
380056.150447726 850758.64105311
#Sta/Elev= 30
9060.66860.502159115.14149.730189155.20445.196259255.362 39.14969265.606 35.4336
9378.81930.60403 9446.9825.212299569.87623.355749645.91525.16695 9669.3423.94097
9751.32926.642439763.04128.666929833.31731.540079950.44331.760239961.55128.97377
9973.71222.682179996.83915.5147810013.4916.5377910073.2327.0689910093.1427.88598
 10170.326.4168910312.1927.7618510343.7526.4907710366.8828.7108610598.1634.12353
10670.6340.3376510806.3147.1534110829.4352.5176810852.5660.1557410877.0260.56652
#Mann= 3 , 0 , 0
9060.668    0.04       09060.668    0.04       010877.02    0.04       0
#XS Ineff= 2 , 0
       0 9857.21           10104       0
Bank Sta=9060.668,10877.02
Exp/Cntr=0.3,0.1

Type RM Length L Ch R = 3 ,6638.322,,,
BEGIN DESCRIPTION:
END DESCRIPTION:
Bridge Culvert--1,0,-1,-1, 0
Deck Dist Width WeirC Skew NumUp NumDn MinLoCord MaxHiCord MaxSubmerge Is_Ogee
61.087900,22.309700,2.6,0, 60, 60, , , 0.95, 0, 0,0,,
 9058.96 9068.20 9078.26 9088.33 9098.39 9128.58 9138.64 9168.83 9188.96 9199.02
 9209.08 9219.15 9229.21 9239.27 9249.34 9259.40 9279.53 9289.59 9299.65 9307.83
 9472.59 9599.75 9703.80 9829.74 9981.46 9981.4610018.5410018.5410069.6510103.93
10280.7110343.8410355.2610363.4310378.1110384.1110400.9610404.7910503.7810538.14
10568.6510607.6210667.7810700.2710707.4310723.4310747.0910758.1810766.9110781.34
10792.9210850.8310873.9910885.5710897.1510908.7310931.8910943.4710955.0510961.93
   58.24   56.40   53.32   51.88   49.44   45.37   44.87   42.16   42.23   41.12
   41.60   40.19   38.14   36.64   36.58   35.53   32.26   29.08   28.07   28.19
   25.62   24.55   25.17   27.95   29.88   29.88   29.75   29.75   29.37   29.57
   27.18   27.29   27.90   27.62   27.93   27.34   27.12   27.56   28.20   28.92
   29.02   29.66   31.52   33.32   34.77   36.03   37.37   36.82   37.98   41.39
   41.77   45.18   46.97   50.47   57.65   58.46   58.87   59.75   65.02   68.84
 -941.76 -943.60 -946.68 -948.12 -950.56 -954.63 -955.13 -957.84 -957.77 -958.88
 -958.40 -959.81 -961.86 -963.36 -963.42 -964.47 -967.74 -970.92 -971.93 -971.81
 -974.38 -975.45 -974.83 -972.05 -970.12   27.38   27.25 -970.25 -970.63 -970.43
 -972.82 -972.71 -972.10 -972.38 -972.07 -972.66 -972.88 -972.44 -971.80 -971.08
 -970.98 -970.34 -968.48 -966.68 -965.23 -963.97 -962.63 -963.18 -962.02 -958.61
 -958.23 -954.82 -953.03 -949.53 -942.35 -941.54 -941.13 -940.25 -934.98 -931.16
 9058.96 9068.20 9078.26 9088.33 9098.39 9128.58 9138.64 9168.83 9188.96 9199.02
 9209.08 9219.15 9229.21 9239.27 9249.34 9259.40 9279.53 9289.59 9299.65 9307.83
 9472.59 9599.75 9703.80 9829.74 9981.46 9981.4610018.5410018.5410069.6510103.93
10280.7110343.8410355.2610363.4310378.1110384.1110400.9610404.7910503.7810538.14
10568.6510607.6210667.7810700.2710707.4310723.4310747.0910758.1810766.9110781.34
10792.9210850.8310873.9910885.5710897.1510908.7310931.8910943.4710955.0510961.93
   58.24   56.40   53.32   51.88   49.44   45.37   44.87   42.16   42.23   41.12
   41.60   40.19   38.14   36.64   36.58   35.53   32.26   29.08   28.07   28.19
   25.62   24.55   25.17   27.95   29.88   29.88   29.75   29.75   29.37   29.57
   27.18   27.29   27.90   27.62   27.93   27.34   27.12   27.56   28.20   28.92
   29.02   29.66   31.52   33.32   34.77   36.03   37.37   36.82   37.98   41.39
   41.77   45.18   46.97   50.47   57.65   58.46   58.87   59.75   65.02   68.84
 -941.76 -943.60 -946.68 -948.12 -950.56 -954.63 -955.13 -957.84 -957.77 -958.88
 -958.40 -959.81 -961.86 -963.36 -963.42 -964.47 -967.74 -970.92 -971.93 -971.81
 -974.38 -975.45 -974.83 -972.05 -970.12   27.38   27.25 -970.25 -970.63 -970.43
 -972.82 -972.71 -972.10 -972.38 -972.07 -972.66 -972.88 -972.44 -971.80 -971.08
 -970.98 -970.34 -968.48 -966.68 -965.23 -963.97 -962.63 -963.18 -962.02 -958.61
 -958.23 -954.82 -953.03 -949.53 -942.35 -941.54 -941.13 -940.25 -934.98 -931.16
BR Coef=-1 , 0 , 0 ,, 0 ,,,0.8,0,1,0,
WSPro=,,,, 1 ,,,, 0 ,,,, 0 ,,,,-1 ,-1 ,-1 , 0 , 0 , 0 , 0 , 0
BC Design=,, 0 ,, 0 ,,,,,,

Type RM Length L Ch R = 1 , 6575.77,222.732200,222.732200,222.732200
XS GIS Cut Line= 6
378543.613027394849731.063974425378574.409258962850012.211501285
379146.428225487850365.585497573379796.428225517850736.418830901
380040.872669995850843.363275334380053.372669965850844.752164245
#Sta/Elev= 30
9001.15758.887819115.77439.826819186.19336.155879206.31332.840959216.373 29.2272
9256.61228.421839276.73125.061969309.06825.953649348.293 22.07169636.12422.46576
9647.92321.098319671.522 24.20589683.321 22.94549942.90824.895499954.70726.50816
9977.77422.57839 10000.814.3910510012.3117.1561410023.8326.9793410058.3624.68788
10278.0922.6026510599.4723.1179110668.5526.3369810714.0932.2496610735.9232.44998
10757.7536.1314710834.1642.00242 10866.946.4612610965.1467.3978610984.1381.06926
#Mann= 3 , 0 , 0
9001.157    0.04       09001.157    0.04       010984.13    0.04       0
#XS Ineff= 2 , 0
       09936.739        10091.62       0
Bank Sta=9001.157,10984.13
Exp/Cntr=0.3,0.1

Type RM Length L Ch R = 1 ,6353.038,479.571600,479.571600,479.571600
XS GIS Cut Line= 2
378233.179537952850051.658631414379748.804537952850999.575298086
#Sta/Elev= 30
9017.54228.754549066.86829.553379078.66322.818499090.45819.003199102.25219.36275
9114.04724.040659125.842 24.45329137.63722.865289161.22625.203519174.71323.48036
9231.99522.655849491.47921.133899597.63221.368339633.01622.906779798.14322.59494
9966.77624.504629975.06424.401919986.85918.3542410004.4916.4572110023.3524.76226
10098.7922.7190610281.7320.6580910317.1121.5574410381.67 19.695210411.4721.23315
10645.6921.33593 10683.423.4502110729.9328.5798610753.5233.0320910805.1840.29676
#Mann= 3 , 0 , 0
9017.542    0.04       09017.542    0.04       010805.18    0.04       0
#XS Ineff= 2 , 0
       09755.845        10182.74       0
Bank Sta=9017.542,10805.18
Exp/Cntr=0.3,0.1

Type RM Length L Ch R = 1 ,5873.466,259.978400,259.978400,259.978400
XS GIS Cut Line= 4
378185.783704609850339.549256429378646.721204594850662.465923086
378784.742037937850774.445089743379081.617037937851240.590923086
#Sta/Elev= 30
9336.13829.380559363.06730.19979 9445.0727.42807 9457.2823.463299467.63822.75104
 9554.7820.948999763.92220.247379774.73421.203669799.15420.35048  9934.722.92623
9973.98121.821499998.18812.4797810014.0617.3850110038.37 20.584910219.59 19.9756
10361.8617.3460710373.7217.4401410385.58 19.343710409.2914.7192210421.1415.09446
   1043318.2690210468.5722.0672310480.4224.6936910492.2834.4347510515.9943.88667
10542.5457.2083510587.13 84.971510610.8498.0301910622.69102.848110629.32 104.224
#Mann= 3 , 0 , 0
9336.138    0.04       09336.138    0.04       010629.32    0.04       0
#XS Ineff= 2 , 0
       09700.717                       0
Bank Sta=9336.138,10629.32
Exp/Cntr=0.3,0.1

Type RM Length L Ch R = 1 ,5613.488,203.906200,203.906200,203.906200
XS GIS Cut Line= 2
378149.325371275850474.965923072378925.367037943851266.632589787
#Sta/Elev= 30
 9484.3232.951949512.37429.25484 9540.3823.82556 9582.3921.742799606.708 23.5532
9638.40320.711239649.56320.722799663.84815.474499678.13414.090199694.416 15.6588
9706.70419.465319720.98920.718929848.45219.411919862.45620.524229963.83821.13145
9974.48221.0132410002.4913.6819910006.6913.6306810016.49 14.386710035.2620.05973
 10044.520.6883410184.5318.3412510352.5717.7852310422.5916.4536910478.1117.90936
 10492.621.6400110506.6822.9439210520.6126.8189610534.6137.1471310592.9172.51328
#Mann= 3 , 0 , 0
 9484.32    0.04       0 9484.32    0.04       010592.91    0.04       0
#XS Ineff= 2 , 0
       09668.844                       0
Bank Sta=9484.32,10592.91
Exp/Cntr=0.3,0.1