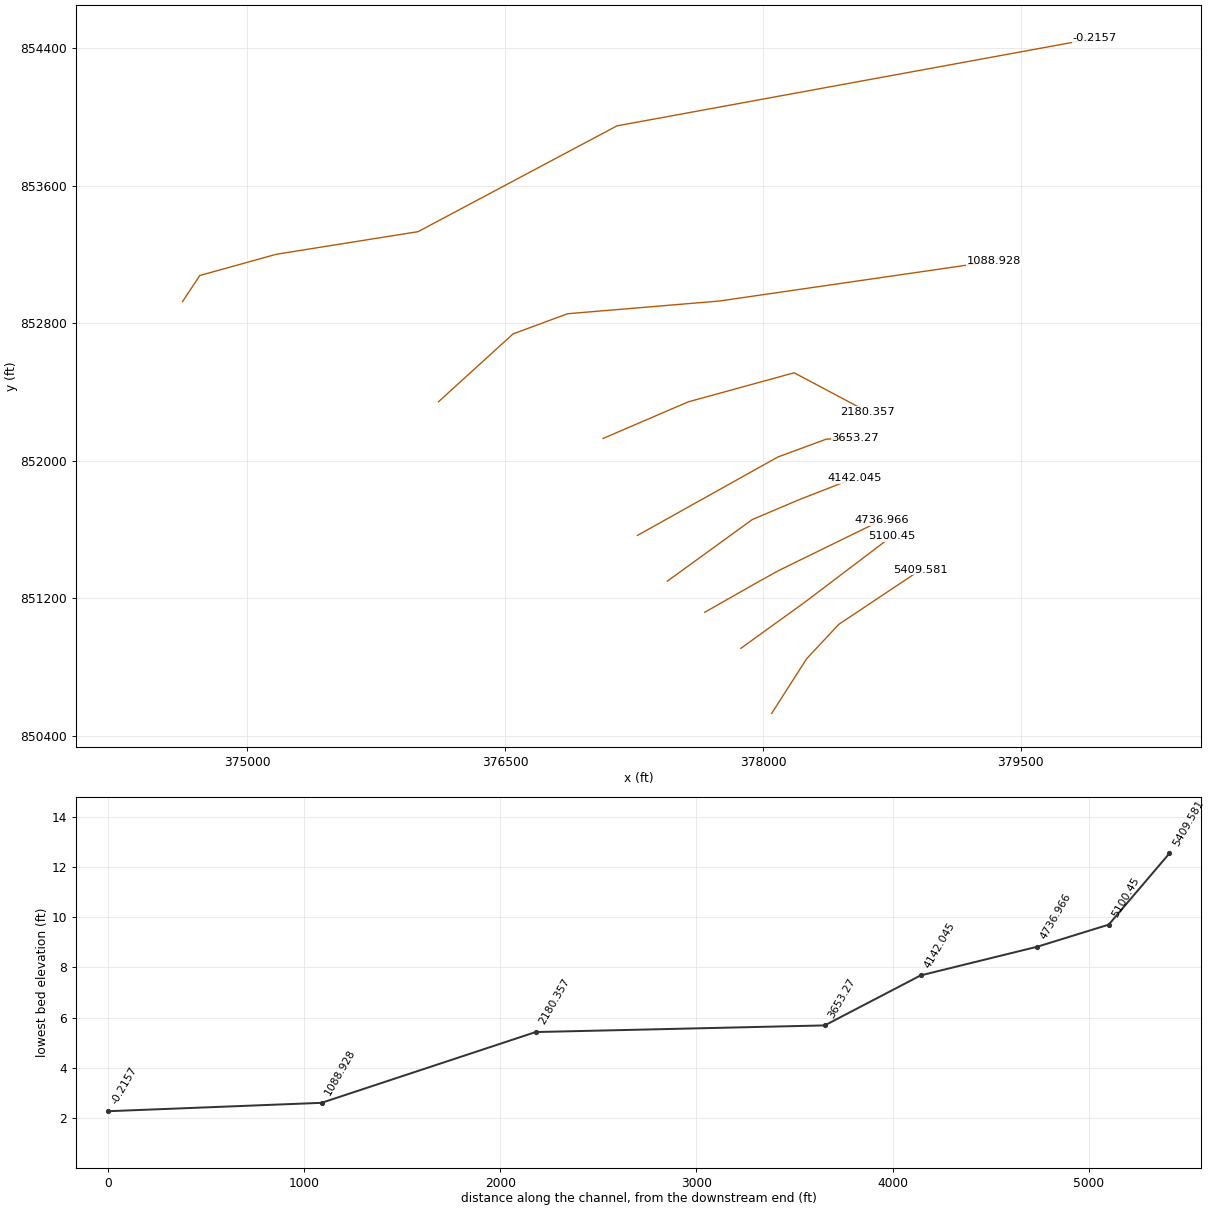
HEC-RAS study 6641_ras.prj: 6641

--- 6641_ras.g01 (geometry) --- (continued)

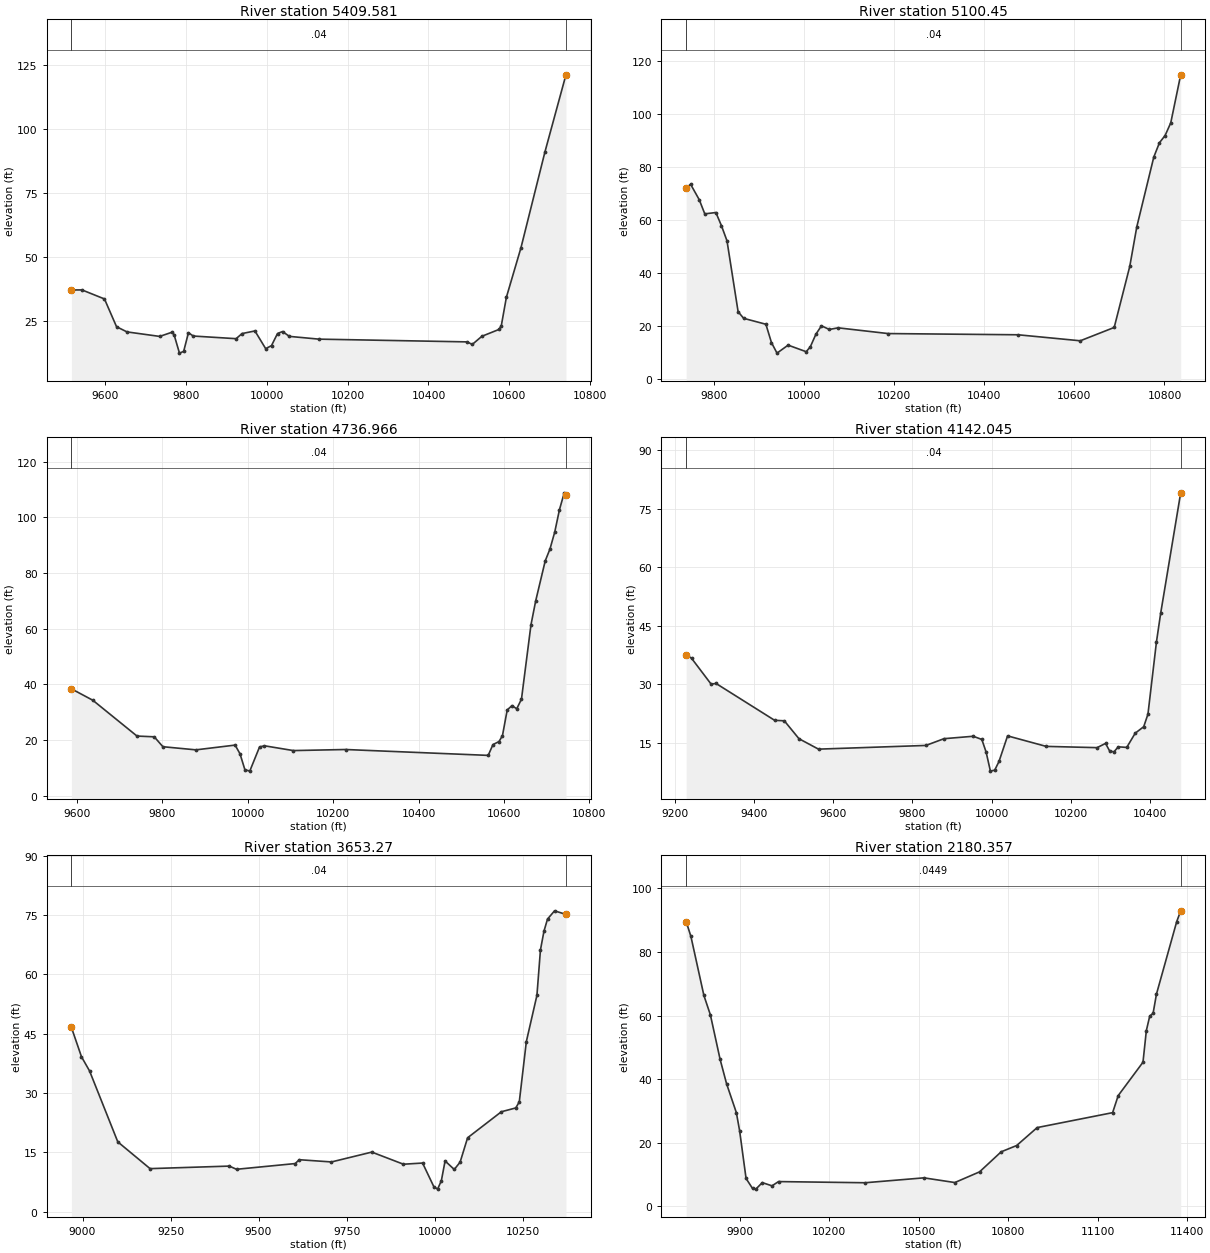
Type RM Length L Ch R = 1 ,5409.581,309.130800,309.130800,309.130800
XS GIS Cut Line= 4
378050.887871265850530.825298101378254.012871265850848.533631414
378441.512871265851049.054464757378918.075371265851366.762798101
#Sta/Elev= 30
9515.932  37.225 9542.1337.244529597.82433.715149627.70922.866979653.51720.84078
9734.53119.078919764.90420.707919770.13819.764399783.46912.548299793.87713.22354
9805.746 20.53069817.61519.226099923.75218.191289938.39320.18908 9970.3321.21673
9996.95914.28469 10011.415.4973610026.2420.2024610038.7820.9895910055.5219.09213
10128.73 18.013310496.2416.9390610508.2615.92326 10532.319.1374210574.8821.82269
10580.3723.3266710592.9134.3870710628.9653.7159810688.5491.2910910740.31121.2797
#Mann= 3 , 0 , 0
9515.932    0.04       09515.932    0.04       010740.31    0.04       0
#XS Ineff= 2 , 0
       09656.775                       0
Bank Sta=9515.932,10740.31
Exp/Cntr=0.3,0.1

Type RM Length L Ch R = 1 , 5100.45,363.484600,363.484600,363.484600
XS GIS Cut Line= 3
377871.460859828850909.205865029378241.830849617851176.259925012
378752.580579586851563.247173046
#Sta/Elev= 30
 9738.6172.227089748.51773.53559 9767.6367.726599779.95862.362279804.61562.85849
9816.94457.882969829.27252.163339853.92925.359489866.25822.860089915.57120.62585
  9927.913.704449940.2289.7069919964.88512.7298310004.9910.24336 10014.212.10834
10026.5316.8525110038.8620.0358510056.2818.6515810075.8419.26985 10186.817.10308
10475.2116.6449910613.2214.37278 10688.519.4163610723.0142.4912110738.6857.49662
10776.3283.8175710788.8789.2440410801.4291.9761910813.9696.7527110836.02114.9188
#Mann= 3 , 0 , 0
 9738.61    0.04       0 9738.61    0.04       010836.02    0.04       0
#XS Ineff= 2 , 0
       0                               0
Bank Sta=9738.61,10836.02
Exp/Cntr=0.3,0.1

Type RM Length L Ch R = 1 ,4736.966,594.920900,594.920900,594.920900
XS GIS Cut Line= 4
377661.409139176851119.006506545 377965.02521929851291.741237458
378092.219109791851362.188008125378688.573276163 851653.85462678
#Sta/Elev= 30
9586.75338.383159636.90534.284629740.45121.418979780.87721.150619801.09917.59434
9878.51216.466149970.33218.177159981.76315.044899993.1959.35407410004.638.827581
10027.4917.4874810038.9217.9291910106.8316.2064210229.2816.5898610563.2414.48029
10574.37 18.360310588.6119.4587210596.6321.5834110607.76 30.8072 10618.932.35173
10630.0331.2148710641.1634.6803310663.42 61.376410674.5670.0367410696.8284.34895
10707.95 88.610810719.08 94.679210730.21102.765110741.35108.774610745.32107.9701
#Mann= 3 , 0 , 0
9586.753    0.04       09586.753    0.04       010745.32    0.04       0
#XS Ineff= 2 , 0
       09941.334                       0
Bank Sta=9586.753,10745.32
Exp/Cntr=0.3,0.1

Type RM Length L Ch R = 1 ,4142.045,488.775300,488.775300,488.775300
XS GIS Cut Line= 4
377443.816158524851300.170659086377937.788419275851658.421171125
378210.247090812851773.953349766378532.194389908851899.509111631
#Sta/Elev= 30
9227.12937.602429240.94436.623699290.35630.002649302.70930.182469450.94620.72966
9475.65220.589939512.71115.998119562.123 13.32399833.89114.272049879.80316.00656
9953.78716.628389975.51115.809189986.37312.572419997.2357.682086 10008.17.932917
10018.9610.1547210040.6816.7262110138.3814.0309810267.1813.7075810288.6514.79002
10299.3812.7878410310.1112.6476510320.8513.9190710342.3213.7669310363.7817.42454
10385.2519.0778910395.98 22.302710417.4540.7979510428.1848.1890410478.8479.09283
#Mann= 3 , 0 , 0
9227.129    0.04       09227.129    0.04       010478.84    0.04       0
#XS Ineff= 2 , 0
       0 9750.25                       0
Bank Sta=9227.129,10478.84
Exp/Cntr=0.3,0.1

Type RM Length L Ch R = 1 , 3653.27,1472.912700,1472.912700,1472.912700
XS GIS Cut Line= 4
377269.941690713851566.285367519378085.913912952852022.014534205
378368.031968489852126.181200877378537.302801818852134.861756429
#Sta/Elev= 30
8968.32946.604628997.03139.156379019.93935.575519100.11717.641979191.74810.87211
9416.87111.512899437.37910.704089604.091  12.1529615.545 13.12569707.17712.56253
9821.71715.053899911.56111.986159965.92612.284619997.9066.30286710008.575.687454
10019.237.79526910029.8912.8130310055.9110.6632810072.5312.5054110093.85 18.6775
10189.7825.2578910230.6826.2210810240.6927.7732310260.7243.0121110290.7654.69323
10300.7766.1842510310.7870.93026 10320.873.9852210340.8276.0731510373.1775.16799
#Mann= 3 , 0 , 0
8968.329    0.04       08968.329    0.04       010373.17    0.04       0
#XS Ineff= 2 , 0
       09356.175                       0
Bank Sta=8968.329,10373.17
Exp/Cntr=0.3,0.1

Type RM Length L Ch R = 1 ,2180.357,1091.429300,1091.429300,1091.429300
XS GIS Cut Line= 4
377070.288912922852130.521478638377565.080579594852343.195089743
378181.400024056852512.465923101 378606.74724628852286.771478638
#Sta/Elev= 30
9719.80689.599849735.81984.899229779.35766.338259801.12660.23959 9833.7846.23028
9855.54938.535699888.20329.503889899.08823.853079920.857 8.768349942.6265.622363
9953.5115.422686 9975.287.46877210007.936.460716 10029.77.79624810320.517.429819
10517.548.97128510621.247.49447710704.2110.85203 10776.817.1630510828.6519.13393
10897.5124.7801111150.6429.4768611169.4634.8516611252.5245.3382311263.8455.30455
11275.1659.8396911286.4860.73829 11297.866.7843611365.7389.5712311379.0392.95927
#Mann= 3 , 0 , 0
9719.806  0.0449       09719.806  0.0449       011379.03  0.0449       0
#XS Ineff= 2 , 0
       0                10451.83       0
Bank Sta=9719.806,11379.03
Exp/Cntr=0.3,0.1

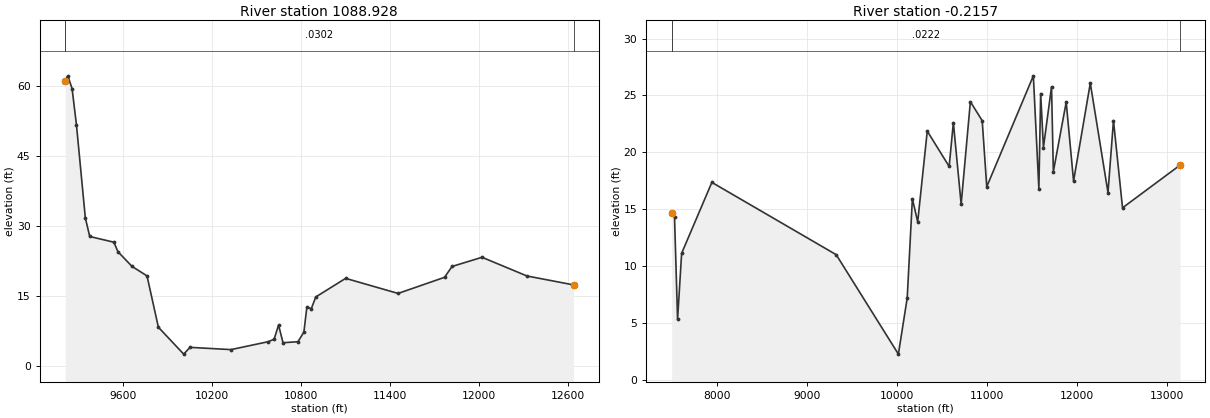
Type RM Length L Ch R = 1 ,1088.928,1089.143400,1089.143400,1089.143400
XS GIS Cut Line= 5
376112.154509011852343.791877948376546.182286804 852738.75715576
376863.022564568852855.944655718377744.098953451852929.729377948
 379345.58714875853161.765080109
#Sta/Elev= 30
9210.77761.233269228.14562.275339257.14659.530719286.86251.686299346.29431.85098
 9376.0127.823559539.12226.596069566.16324.563579660.80921.421929762.316   19.37
9839.0028.362932 10009.62.59913610052.244.05121810328.083.56797710578.965.260126
 10619.1 5.79161 10649.28.82305310679.315.04336710779.665.259022 10819.87.301074
10839.8712.6565910869.9712.3562310900.0814.8563311101.3418.8477811454.9915.61235
11768.23 19.069911818.7521.3970412020.8423.3654812323.9719.35476 12637.817.44573
#Mann= 3 , 0 , 0
9210.777  0.0302       09210.777  0.0302       0 12637.8  0.0302       0
#XS Ineff= 2 , 0
       09901.224        10470.54       0
Bank Sta=9210.777,12637.8
Exp/Cntr=0.3,0.1

Type RM Length L Ch R = 1 , -0.2157,0.000000,0.000000,0.000000
XS GIS Cut Line= 6
374623.036453422852926.807936988374723.730897861853078.500645282
375169.694439536853202.198561976 375993.26214786853333.491964774
 377150.78298121853949.188290014379929.732550026854458.313172246
#Sta/Elev= 30
7494.70214.62447 7526.46  14.2917560.2555.3084727605.31511.123767940.92517.35709
9321.84711.0021410012.29 2.2640410110.347.198295 10167.715.9207110226.8213.88733
10332.8621.8620710576.2518.7540210622.75  22.609 10709.315.44857 10811.7 24.4479
 10943.122.7800410993.4516.9739911511.0726.7202111572.4116.78569 11592.325.15983
11622.9820.4151611712.98 25.764311733.2318.2985311875.8924.4082911957.5917.46672
12143.3926.0712712339.9316.4638312400.7822.7896412501.3215.1201613139.55 18.8688
#Mann= 3 , 0 , 0
7494.702  0.0222       07494.702  0.0222       013139.55  0.0222       0
#XS Ineff= 2 , 0
       09928.303        10068.76       0
Bank Sta=7494.702,13139.55
Exp/Cntr=0.3,0.1